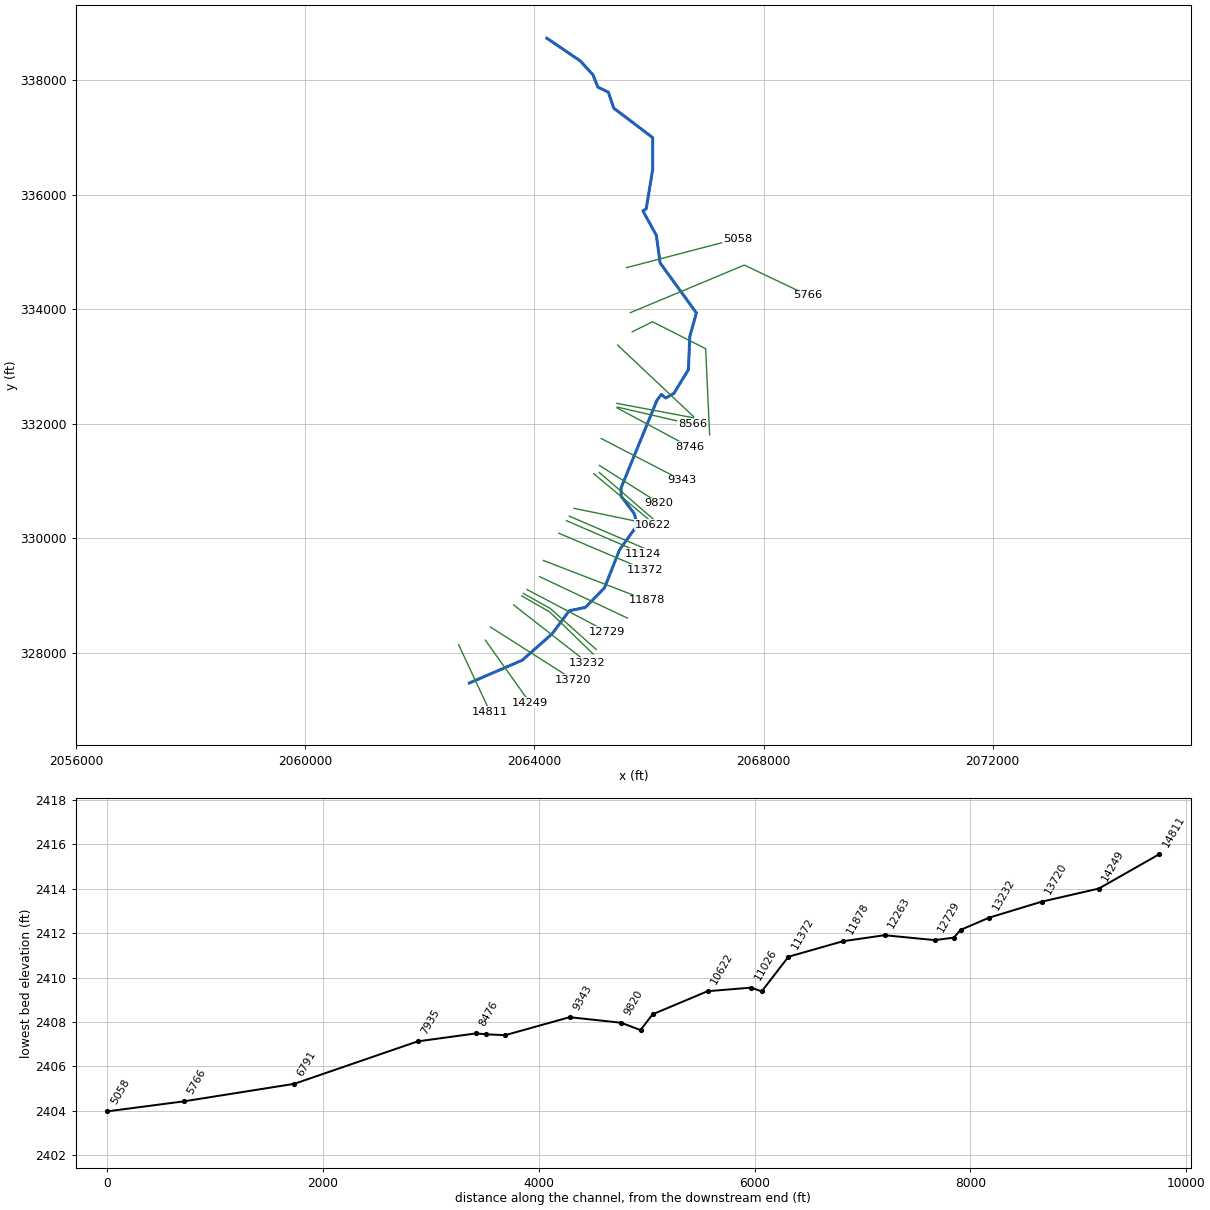
--- MTHODSTBR.prj (project) ---

Proj Title=MTHODSTBR
Current Plan=p01
Default Exp/Contr=0.3,0.1
English Units
Geom File=g01
Flow File=f01
Plan File=p01
Y Axis Title=Elevation
X Axis Title(PF)=Main Channel Distance
X Axis Title(XS)=Station
BEGIN DESCRIPTION:
Stream Name- Methodist Branch
Flood Zone: Zone A
Greenbrier County, WV
County-Wide Study
WVDHSEM-2018-3, Flood Risk Project
HEC-RAS Version: 5.0.7
General Notes:
For the Hydrology regression was used.
END DESCRIPTION:
DSS File=dss
DSS Export Rating Curves= 0
DSS Export Rating Curve Sorted= 0
DSS Export Volume Flow Curves= 0
DXF Filename=..\H2c.
DXF OffsetX= 0
DXF OffsetY= 0
DXF ScaleX= 1
DXF ScaleY= 10

--- MTHODSTBR.p01 (plan) ---

Plan Title=Floodplain
Program Version=5.07
Short Identifier=Floodplain
Geom File=g01
Flow File=f01
Subcritical Flow
K Sum by GR= 0
Std Step Tol= 0.01
Critical Tol= 0.01
Num of Std Step Trials= 20
Max Error Tol= 0.3
Flow Tol Ratio= 0.001
Split Flow NTrial= 30
Split Flow Tol= 0.02
Split Flow Ratio= 0.02
Log Output Level= 0
Friction Slope Method= 1
Unsteady Friction Slope Method= 2
Unsteady Bridges Friction Slope Method= 1
Parabolic Critical Depth
Global Vel Dist= 0 , 0 , 0
Global Log Level= 0
CheckData=True
Encroach Param=-1 ,0,0, 0
Computation Interval=1MIN
Output Interval=1HOUR
Instantaneous Interval=1HOUR
Mapping Interval=1HOUR
Computation Time Step Use Courant=        0
Computation Time Step Use Time Series=    0
Computation Time Step Count To Double=0
Computation Time Step Max Doubling=0
Computation Time Step Max Halving=0
Computation Time Step Residence Courant=0
Run HTab= 0
Run UNet= 0
Run Sediment= 0
Run PostProcess= 0
Run WQNet= 0
Run RASMapper= 0
UNET Theta= 1
UNET Theta Warmup= 1
UNET ZTol= 0.02
UNET ZSATol= 0.02
UNET MxIter= 20
UNET Max Iter WO Improvement= 0
UNET MaxInSteps= 0
UNET DtIC= 0
UNET DtMin= 0
UNET MaxCRTS= 20
UNET WFStab= 2
UNET SFStab= 1
UNET WFX= 1
UNET SFX= 1
UNET 1D Methodology=Finite Difference
UNET DSS MLevel= 4
UNET Pardiso=0
UNET DZMax Abort= 100
UNET Use Existing IB Tables=-1
UNET Froude Reduction=False
UNET Froude Limit= 0.8
UNET Froude Power= 4
UNET D1 Cores= 0
UNET D2 Coriolis=0
UNET D2 Cores= 0
UNET D2 Theta= 1
UNET D2 Theta Warmup= 1
UNET D2 Z Tol= 0.01
UNET D2 Volume Tol= 0.01
UNET D2 Max Iterations= 20
UNET D2 Equation= 0
UNET D2 RampUpFraction=0.1
UNET D2 TimeSlices= 1
UNET D2 BCVolumeCheck=0
UNET D1D2 MaxIter= 0
UNET D1D2 ZTol=0.01
UNET D1D2 QTol=0.1
UNET D1D2 MinQTol=1
DSS File=dss
Write IC File= 0
Write IC File at Fixed DateTime=0
Write IC File at Sim End=0
Echo Input=False
Echo Parameters=False
Echo Output=False
Write Detailed= 0
HDF Write Warmup=0
HDF Write Time Slices=0
HDF Flush=0
HDF Face Node Velocities=0
HDF Compression= 1
HDF Chunk Size= 1
HDF Spatial Parts= 1
HDF Use Max Rows=0
HDF Fixed Rows= 1
Calibration Method= 0
Calibration Iterations= 20
Calibration Max Change=0.05
Calibration Tolerance=0.2
Calibration Maximum=1.5
Calibration Minimum=0.5
Calibration Optimization Method= 1
WQ AD Non Conservative
WQ ULTIMATE=-1
WQ Max Comp Step=1HOUR
WQ Output Interval=15MIN
WQ Output Selected Increments= 0
WQ Output face flow=0
WQ Output face velocity=0
WQ Output face area=0
WQ Output face dispersion=0
WQ Output cell volume=0
WQ Output cell surface area=0
WQ Output cell continuity=0
WQ Output cumulative cell continuity=0
WQ Output face conc=0
WQ Output face dconc_dx=0
WQ Output face courant=0
WQ Output face peclet=0
WQ Output face adv mass=0
WQ Output face disp mass=0
WQ Output cell mass=0
WQ Output cell source sink temp=0
WQ Output nsm pathways=0
WQ Output nsm derived pathways=0
WQ Output MaxMinRange=-1
WQ Daily Max Min Mean=-1
WQ Daily Range=0
WQ Daily Time=0
WQ Create Restart=0
WQ Fixed Restart=0
WQ System Summary=0
WQ Write To DSS=0
WQ Use Fixed Temperature=0
Sorting and Armoring Iterations= 10
XS Update Threshold= 0.02
Bed Roughness Predictor= 0
Hydraulics Update Threshold= 0.02
Energy Slope Method= 1
Volume Change Method= 1
Sediment Retention Method= 0
XS Weighting Method= 0
Number of US Weighted Cross Sections= 1
Number of DS Weighted Cross Sections= 1
Upstream XS Weight=0
Main XS Weight=1
Downstream XS Weight=0
Number of DS XS's Weighted with US Boundary= 1
Upstream Boundary Weight= 1
Weight of XSs Associated with US Boundary= 0
Number of US XS's Weighted with DS Boundary= 1
Downstream Boundary Weight= 0.5
Weight of XSs Associated with DS Boundary= 0.5
Percentile Method= 0
Sediment Output Level= 3
Mass or Volume Output= 0
Output Increment Type= 1
Profile and TS Output Increment= 1
XS Output Flag= 0
XS Output Increment= 10
Write Gradation File= 0
Read Gradation Hotstart= 0
Write HDF5 File= 1
Write Binary Output= 1
Write DSS Sediment File= 0
SV Curve= 0
Specific Gage Flag= 0

--- MTHODSTBR.f01 (steady flow) ---

Flow Title=H2c
Program Version=5.07
Number of Profiles= 6
Profile Names=f1p,f10p,f4p,f2p,f02p,f1pplus
River Rch & RM=MTHODSTBR,Main            ,14811
     498     262     349     422     698     737
River Rch & RM=MTHODSTBR,Main            ,14249
     565     298     397     478     790     836
River Rch & RM=MTHODSTBR,Main            ,10622
     656     348     462     556     914     970
River Rch & RM=MTHODSTBR,Main            ,5766
    2710    1520    1960    2320    3680    4010
Boundary for River Rch & Prof#=MTHODSTBR,Main            , 1
Up Type= 0
Dn Type= 3
Dn Slope=0.00015
Boundary for River Rch & Prof#=MTHODSTBR,Main            , 2
Up Type= 0
Dn Type= 3
Dn Slope=0.00015
Boundary for River Rch & Prof#=MTHODSTBR,Main            , 3
Up Type= 0
Dn Type= 3
Dn Slope=0.00015
Boundary for River Rch & Prof#=MTHODSTBR,Main            , 4
Up Type= 0
Dn Type= 3
Dn Slope=0.00015
Boundary for River Rch & Prof#=MTHODSTBR,Main            , 5
Up Type= 0
Dn Type= 3
Dn Slope=0.00015
Boundary for River Rch & Prof#=MTHODSTBR,Main            , 6
Up Type= 0
Dn Type= 3
Dn Slope=0.00015
DSS Import GetInterval= 0
DSS Import GetPeak= 0
DSS Import FillOption= 0

--- MTHODSTBR.g01 (geometry) ---

Geom Title=H2c
Program Version=5.07

River Reach=MTHODSTBR       ,Main
Reach XY= 30
     2062864.566      327473.145     2063786.888      327871.071
      2064309.35      328332.992     2064608.079      328735.786
     2064889.282       328793.29 2065221.8915746329134.089354503
2065485.40922009329797.537212702     2065793.972      330227.842
     2065745.632      330426.675     2065513.052      330736.781
     2065513.052      330882.713     2066141.473      332415.003
2066217.27580385332511.596754513 2066292.2909528332450.281977077
2066435.59757753332531.129671168     2066688.345      332946.424
2066712.43277864333525.001885423     2066827.879      333936.287
     2066195.037      334807.418     2066128.852      335290.266
2065894.02712451335717.1890057462065951.35550145335755.243265576
2066063.44527145336435.8874549372066063.52496934336998.302074247
2065384.96194152337511.712176904      2065290.58      337790.819
2065107.08650064337879.942000696     2065022.132      338093.148
2064799.55724991338337.095500058     2064218.164      338732.677

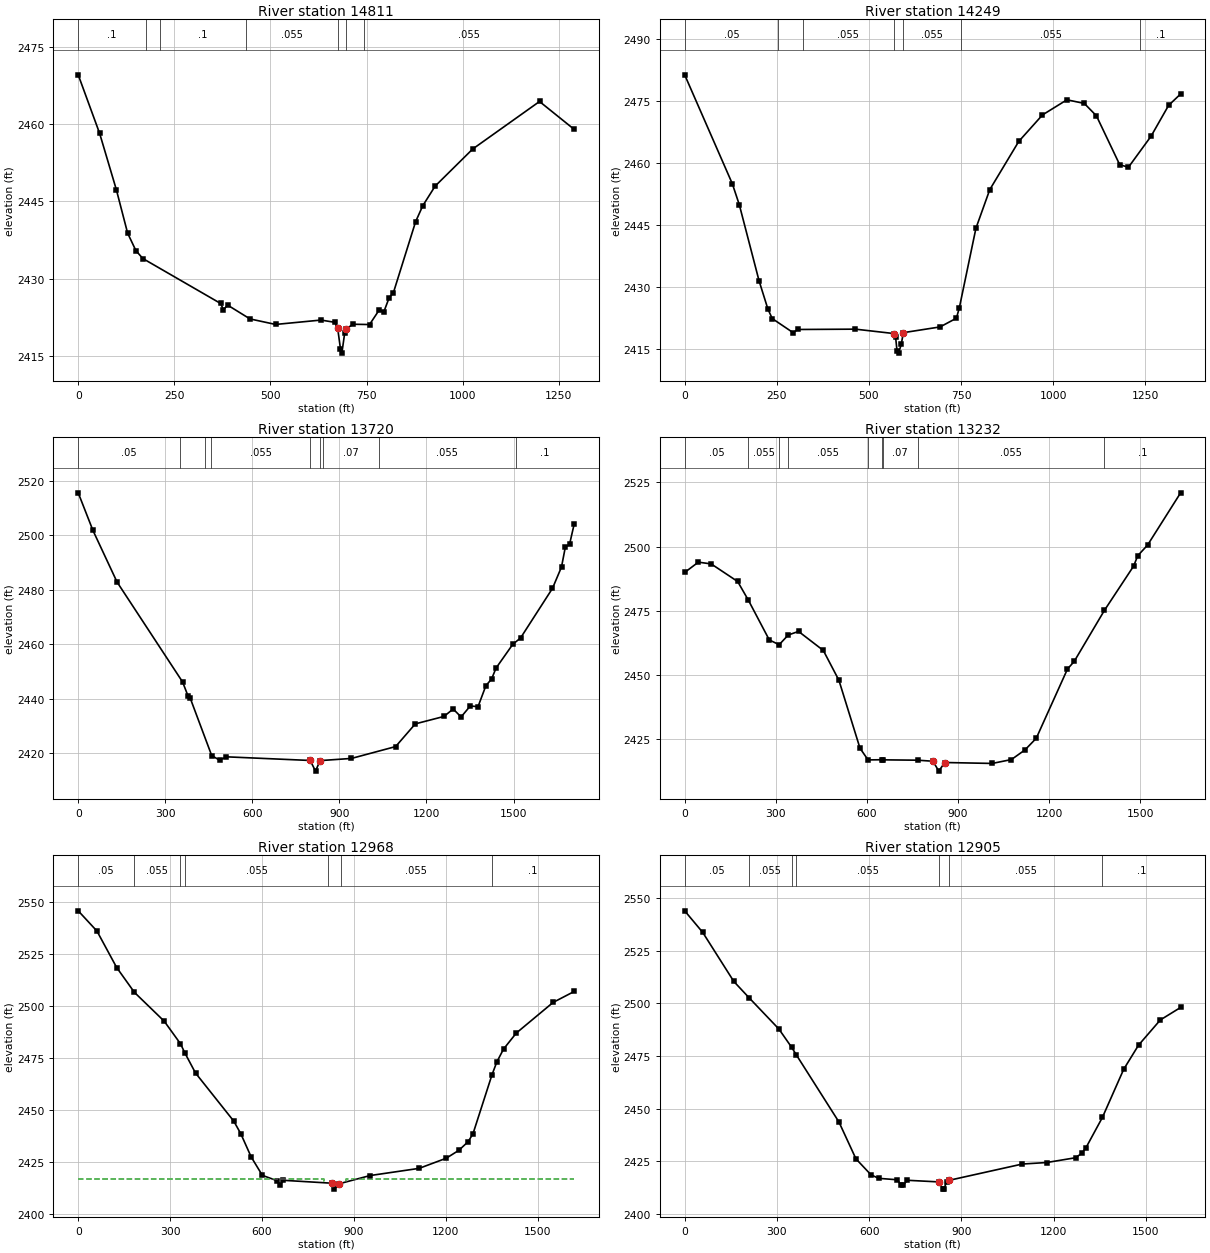
Type RM Length L Ch R = 1 ,14811   ,559.4,561.7,564
XS GIS Cut Line= 2
2062677.04938587328140.4990408862063223.12179254326971.562795359
#Sta/Elev= 30
       0 2469.51    55.8 2458.14    99.3 2447.22   128.5 2438.83     150 2435.44
   168.1  2433.9   370.4 2425.19   377.8 2423.99   388.9 2424.86   446.9 2422.19
   513.5 2421.12   631.6 2421.97   667.8 2421.53     675 2420.37   682.3 2416.37
   685.9 2415.56   693.1 2419.38   696.7 2420.23   714.9 2421.16   757.9  2421.1
   783.7    2424   794.5 2423.44     809 2426.32   819.9 2427.26   877.8 2441.05
   896.5 2444.15   928.5 2447.93  1026.3 2455.13  1200.1 2464.34  1290.2 2458.94
#Mann= 7 ,-1 , 0
       0      .1       0  176.17     .07       0   211.8      .1       0
  436.69    .055       0     675    .045       0   696.7    .055       0
  744.18    .055       0
Bank Sta=675,696.7
XS Rating Curve= 0 ,0
Exp/Cntr(USF)=0,0
Exp/Cntr=0.3,0.1

Type RM Length L Ch R = 1 ,14249   ,523.1,529.3,536.7
XS GIS Cut Line= 2
2063142.06416967328221.5566637522063922.77706358327125.145659735
#Sta/Elev= 30
       0 2481.34   129.4 2454.97   148.3  2449.9   201.8 2431.53     226 2424.63
   237.7 2422.37   294.5 2418.95   306.6 2419.73   463.5 2419.81   568.4 2418.74
   572.4 2417.92   576.4  2414.5   580.4 2414.01   587.8 2416.13   593.4 2418.96
   693.2 2420.35   737.5 2422.46   745.6 2425.04   790.5 2444.23     828 2453.56
   906.7 2465.23   971.1 2471.64  1037.5  2475.3  1084.6 2474.42  1117.5 2471.42
  1180.6 2459.61  1204.3 2458.97  1265.7 2466.48  1313.5 2473.96    1346 2476.71
#Mann= 7 ,-1 , 0
       0     .05       0  254.31      .1       0  319.91    .055       0
   568.4    .045       0   593.4    .055       0  750.27    .055       0
 1236.38      .1       0
Bank Sta=568.4,593.4
XS Rating Curve= 0 ,0
Exp/Cntr(USF)=0,0
Exp/Cntr=0.3,0.1

Type RM Length L Ch R = 1 ,13720   ,488.3,488,486
XS GIS Cut Line= 2
2063235.92036457328447.6647696382064677.89281343 327530.43377406
#Sta/Elev= 30
       0 2515.55    50.7 2501.76   133.9  2482.8   359.7 2446.14   378.7 2440.92
   386.2 2440.14     460 2419.13   487.3 2417.44   510.6 2418.67   799.4 2417.33
   817.8 2413.42   833.3 2417.28   941.6 2418.08  1093.8 2422.43  1161.6 2430.76
  1260.4 2433.49  1292.1 2436.22  1319.4  2433.3  1351.1 2437.34  1377.7 2437.06
  1404.9 2444.79  1424.4 2447.22  1439.9 2451.24  1497.8    2460  1524.2 2462.27
  1634.3 2480.49  1665.4 2488.33  1678.7 2495.68    1693 2496.59    1709 2504.04
#Mann= 9 ,-1 , 0
       0     .05       0  349.38    .055       0  435.23     .05       0
  457.48    .055       0   799.4    .045       0   833.3    .055       0
  842.47     .07       0 1035.82    .055       0 1508.29      .1       0
Bank Sta=799.4,833.3
XS Rating Curve= 0 ,0
Exp/Cntr(USF)=0,0
Exp/Cntr=0.3,0.1

Type RM Length L Ch R = 1 ,13232   ,264.7,263.5,261.6
XS GIS Cut Line= 2
2063637.63475613328835.9900894982064923.70854946327830.004962592
#Sta/Elev= 30
       0 2489.93      45 2493.94    87.3 2493.25   174.4 2486.42   209.8 2479.13
   278.5 2463.72     311 2461.84     341 2465.63   374.9 2467.01   456.4 2459.62
   507.8 2448.02   577.2  2421.6   603.8 2417.06   650.3 2417.13   651.8 2417.09
   767.2 2416.95   817.42416.544   836.7  2412.7     856 2416.05  1012.6 2415.69
  1075.7  2417.2  1120.4 2420.95  1157.5 2425.47  1260.3 2452.39  1282.4 2455.34
  1381.9 2475.19  1478.1 2492.42  1491.7 2496.45    1524 2500.58  1632.8 2520.89
#Mann= 9 ,-1 , 0
       0     .05       0   209.8    .055       0     311     .05       0
     341    .055       0   603.8    .045       0   650.3    .055       0
   651.8     .07       0   767.2    .055       0  1381.9      .1       0
Bank Sta=817.4,856
XS Rating Curve= 0 ,0
Exp/Cntr(USF)=0,0
Exp/Cntr=0.5,0.3

Type RM Length L Ch R = 1 ,12968   ,63.2,63.5,63.7
XS GIS Cut Line= 3
2063777.79862116328995.089786893 2064267.9537874328712.667048248
2065024.19318675327979.768371106
#Sta/Elev= 30
       0 2545.66    61.1 2535.96   125.5 2518.47   183.3 2506.57   280.8  2492.7
   333.8 2481.89   348.4  2477.4     383 2467.83   507.9 2444.74   530.7 2438.72
   564.7 2427.55   601.1 2418.75   648.2 2416.25   659.1  2414.2   669.6 2416.38
   826.8    2415   836.1 2412.15   852.4 2414.75   952.9 2418.67  1112.8 2422.11
  1201.2 2426.97  1242.2 2430.74  1272.7  2434.9  1288.6 2438.71  1350.4 2466.91
  1366.2  2473.1  1388.3 2479.34  1430.1 2487.04  1550.1 2501.72  1618.8 2506.96
#Mann= 7 ,-1 , 0
       0     .05       0   183.3    .055       0   333.8     .05       0
   348.4    .055       0   815.8    .045       0   856.7    .055       0
  1350.4      .1       0
#XS Ineff= 2 , 0
          801.16    2417  873.16            2417
Permanent Ineff=
       F       F
Bank Sta=826.8,852.4
XS Rating Curve= 0 ,0
Exp/Cntr(USF)=0,0
Exp/Cntr=0.5,0.3

Type RM Length L Ch R = 1 ,12905   ,172.8,176.1,181.1
XS GIS Cut Line= 3
 2063805.8074878329037.1030868562064274.95600406328775.686998194
2065077.87684781328059.126826593
#Sta/Elev= 30
       0 2544.01    58.6 2533.78   159.9 2510.45   208.9  2502.8   306.5 2487.85
   347.8  2479.2   362.8 2475.67   501.8 2443.69   557.1 2426.19   605.9 2418.63
   630.8 2416.93   691.9 2416.24   703.5 2413.81   709.6 2413.55   724.4    2416
   826.7 2415.23   840.6  2411.8   843.2 2411.93   852.2 2415.24   858.42415.926
  1098.2 2423.72  1177.7 2424.44  1271.3 2426.71    1291 2428.75  1304.9 2431.36
  1358.8 2445.87    1428 2468.72  1476.4 2480.21  1547.2 2492.17  1613.2 2498.11
#Mann= 7 ,-1 , 0
       0     .05       0   208.9    .055       0   347.8     .05       0
   362.8    .055       0   826.7    .045       0   858.4    .055       0
  1358.8      .1       0
Bank Sta=826.7,858.4
XS Rating Curve= 0 ,0
Exp/Cntr(USF)=0,0
Exp/Cntr=0.5,0.3

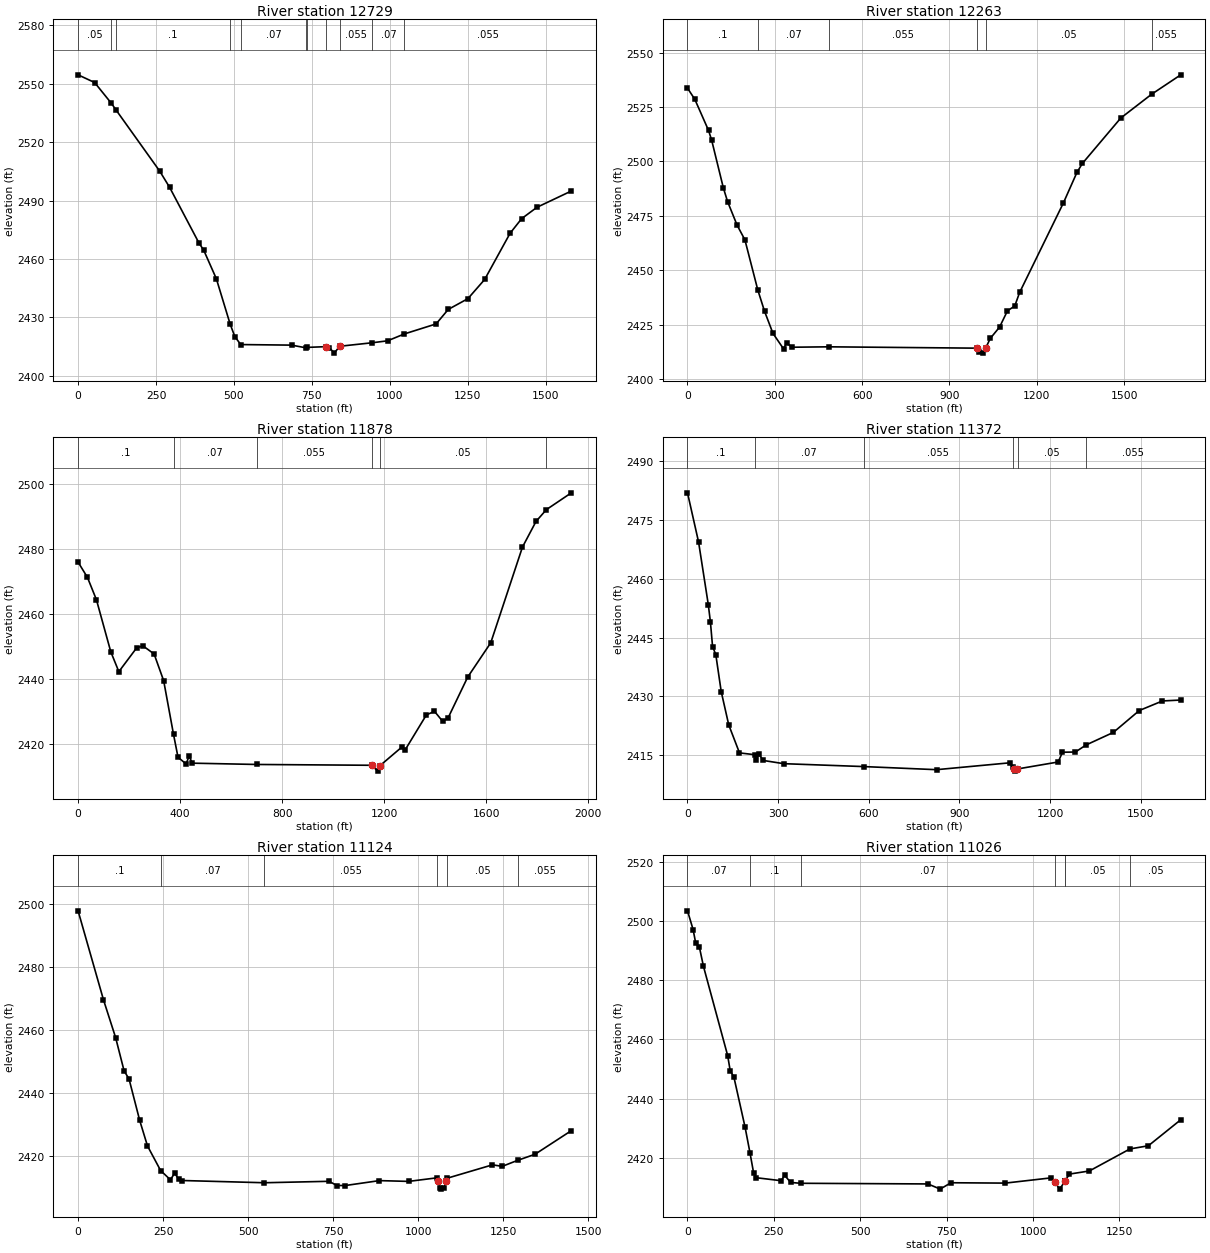
Type RM Length L Ch R = 1 ,12729   ,467.9,465.9,460.9
XS GIS Cut Line= 2
2063871.58277546329104.6581339132065270.89331755328366.607146773
#Sta/Elev= 30
       0 2554.62    53.1 2550.66   106.5 2540.05     121 2536.74   261.7 2505.19
   293.5 2496.86   387.8 2468.22   402.9 2464.58   443.5 2449.88   487.7  2426.6
   502.8 2420.16   521.7 2416.09   684.6  2415.8   732.1 2414.38   735.4 2414.64
   796.1 2415.02   805.9  2414.5   821.8 2411.69   838.9 2415.21   944.1 2417.03
   992.8 2418.02  1046.3 2421.54  1148.3 2426.69  1187.1 2434.12  1250.2 2439.66
    1304 2449.51  1385.6 2473.26  1422.7 2480.77  1471.8 2486.59    1582 2494.95
#Mann= 11 ,-1 , 0
       0     .05       0   106.5      .1       0     121      .1       0
   487.7    .055       0   521.7     .07       0   732.1    .055       0
   735.4     .07       0   796.1    .045       0   838.9    .055       0
   944.1     .07       0  1046.3    .055       0
Bank Sta=796.1,838.9
XS Rating Curve= 0 ,0
Exp/Cntr(USF)=0,0
Exp/Cntr=0.3,0.1

Type RM Length L Ch R = 1 ,12263   ,385.7,385.1,388.3
XS GIS Cut Line= 2
2064090.14617319329330.4347168132065622.79592313328606.981163518
#Sta/Elev= 30
       0 2533.67    25.2 2528.54    72.4 2514.22    83.2 2509.69   123.1  2487.9
   137.7 2481.56   170.3 2470.75   197.3 2463.95   241.6 2440.92   264.6 2431.19
   293.7 2420.98   329.9  2413.9   340.8 2416.57     359 2414.62   485.6 2414.81
   993.62414.193  1001.1 2412.56  1015.5 2411.91  1025.4 2414.45  1040.2 2418.65
  1072.2 2423.86  1099.3 2431.33  1124.5 2433.59  1141.2 2439.79  1291.6 2480.94
  1338.1 2494.95  1356.7 2499.06  1488.7 2519.94  1594.7 2530.88  1694.8  2539.8
#Mann= 6 ,-1 , 0
       0      .1       0   241.6     .07       0   485.6    .055       0
   993.6    .045       0  1025.4     .05       0  1594.7    .055       0
Bank Sta=993.6,1025.4
XS Rating Curve= 0 ,0
Exp/Cntr(USF)=0,0
Exp/Cntr=0.3,0.1

Type RM Length L Ch R = 1 ,11878   ,505.8,505.9,505.5
XS GIS Cut Line= 2
2064157.41755082329612.3348244892065962.01620724 328916.94574412
#Sta/Elev= 30
       0 2475.98    36.7 2471.28    71.9 2464.41   128.1 2448.41   159.8 2442.26
   230.1 2449.63   254.7 2450.18   298.1  2447.7   335.6 2439.46   374.2 2422.95
   391.8 2415.92   423.5 2413.84   435.2 2416.24   448.1 2414.09   701.2 2413.69
  1150.9 2413.44    1175 2411.64  1183.9 2413.34  1268.5 2418.99  1282.9 2418.25
  1365.7 2428.96  1397.4 2430.04    1429 2427.01  1450.1 2427.93  1527.5 2440.58
  1617.9 2451.14  1742.2  2480.6  1795.5 2488.51  1836.1 2492.14  1933.9 2497.31
#Mann= 6 ,-1 , 0
       0      .1       0   374.2     .07       0   701.2    .055       0
  1150.9    .045       0  1183.9     .05       0  1836.1    .055       0
Bank Sta=1150.9,1183.9
XS Rating Curve= 0 ,0
Exp/Cntr(USF)=0,0
Exp/Cntr=0.3,0.1

Type RM Length L Ch R = 1 ,11372   ,247.5,247.5,248.3
XS GIS Cut Line= 2
2064426.88395931330087.8633782962065930.02943959329450.418350548
#Sta/Elev= 30
       0 2481.88    36.7 2469.33    68.8 2453.41    75.8 2449.02      83 2442.68
    93.7 2440.65   111.6 2431.22   136.5 2422.73   172.1 2415.59     222 2415.13
   228.4 2413.65   235.9 2415.28   250.9 2413.66   318.5 2412.84   583.7  2412.1
   824.3 2411.31    1067 2413.06  1077.3 2411.98  1079.2 2411.54  1084.4 2410.94
  1091.7  2411.5  1094.2 2411.52    1227 2413.27  1241.2 2415.76    1284 2415.81
  1319.1  2417.6  1409.6 2420.81  1495.5 2426.39  1572.2 2428.83  1632.7 2429.06
#Mann= 6 ,-1 , 0
       0      .1       0     222     .07       0   583.7    .055       0
  1077.3    .045       0  1094.2     .05       0  1319.1    .055       0
Bank Sta=1079.2,1091.7
XS Rating Curve= 0 ,0
Exp/Cntr(USF)=0,0
Exp/Cntr=0.5,0.3

Type RM Length L Ch R = 1 ,11124   ,97.3,98.3,98.7
XS GIS Cut Line= 2
2064559.52879662330307.6062977012065890.71443396329731.300320562
#Sta/Elev= 30
       0 2497.94    74.6 2469.66   110.4  2457.6   135.4 2446.98   149.7 2444.49
   181.2 2431.25   204.1 2423.12   242.7  2415.3   271.5 2412.35     284 2414.44
   296.5 2412.47     307 2412.12     548 2411.41   738.1 2411.87     761 2410.53
   786.1 2410.53   886.2 2412.09     972 2411.84  1054.2 2412.96  1058.7 2412.04
  1064.9 2409.59  1068.5 2409.38  1075.7 2409.66  1082.8 2411.94  1086.4 2412.88
  1218.7 2417.11  1247.3 2416.63  1293.7 2418.58  1343.8 2420.47  1450.6 2427.99
#Mann= 6 ,-1 , 0
       0      .1       0   242.7     .07       0     548    .055       0
  1054.2    .045       0  1086.4     .05       0  1293.7    .055       0
#XS Ineff= 2 , 0
            1055    2412    1090            2412
Permanent Ineff=
       F       F
Bank Sta=1058.7,1082.8
XS Rating Curve= 0 ,0
Exp/Cntr(USF)=0,0
Exp/Cntr=0.5,0.3

Type RM Length L Ch R = 1 ,11026   ,400.5,403.5,403.5
XS GIS Cut Line= 2
2064609.54642134330386.0907486252065921.44312695329823.395255447
#Sta/Elev= 30
       0 2503.38    16.2 2497.08    23.7 2492.54    34.4 2491.17    46.2 2484.66
   116.2  2454.6   123.6 2449.48   134.3 2447.32   166.5 2430.52   180.7 2421.89
   191.4 2414.98   198.6  2413.4   271.1 2412.39   281.1 2414.22   298.5 2411.81
   327.1 2411.52   695.8  2411.3   731.3 2409.57   762.6  2411.7   919.7 2411.58
  1051.8 2413.34  1062.5  2412.1  1076.8 2409.55  1092.5 2412.19    1093 2412.38
  1105.3 2414.62    1163 2415.67  1280.4  2423.1  1333.8 2424.17  1427.5 2432.94
#Mann= 7 ,-1 , 0
       0     .07       0   180.7      .1       0   327.1     .07       0
  1062.5    .045       0  1092.5    .045       0    1093     .05       0
  1280.4     .05       0
Bank Sta=1062.5,1092.5
XS Rating Curve= 0 ,0
Exp/Cntr(USF)=0,0
Exp/Cntr=0.5,0.3

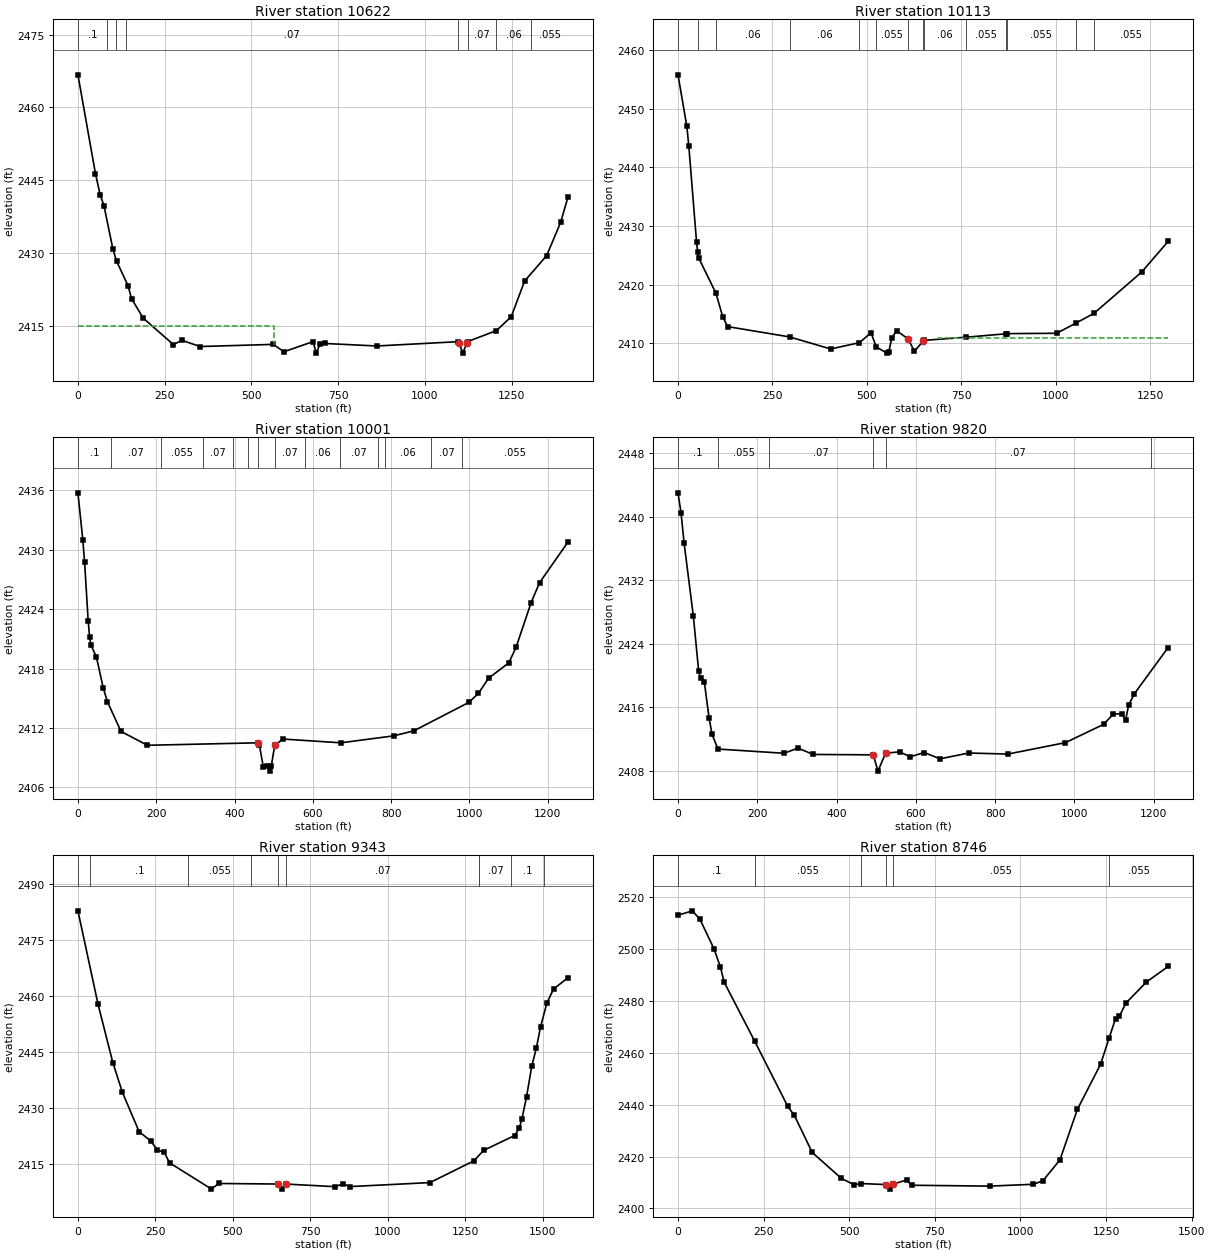
Type RM Length L Ch R = 1 ,10622   ,516.9,509.1,495.9
XS GIS Cut Line= 2
2064689.97642526330524.0485096162066072.98589543330236.866215262
#Sta/Elev= 30
       0  2466.7    50.6 2446.32      64 2442.03      75 2439.77   100.9 2430.78
   111.6  2428.3   144.5 2423.27   154.5 2420.62     188 2416.61   275.1 2411.15
   299.7 2412.02   352.2 2410.75   563.3 2411.19   593.5 2409.67   677.2 2411.75
   687.3 2409.39   697.4 2411.25   710.8 2411.38   861.5 2410.86    1096 2411.75
  1097.22411.524  1109.5 2409.48  1121.5 2411.56  1122.9 2411.76  1206.1 2414.03
  1248.7 2416.88  1287.1 2424.21  1350.8 2429.47    1391 2436.29  1412.5 2441.59
#Mann= 8 ,-1 , 0
       0      .1       0   84.02     .07       0  110.55      .1       0
   138.2     .07       0    1096    .045       0  1122.9     .07       0
  1206.1     .06       0 1305.53    .055       0
#XS Ineff= 2 , 0
          564.16 2414.95
Permanent Ineff=
       F       F
Bank Sta=1097.2,1121.5
XS Rating Curve= 0 ,0
Exp/Cntr(USF)=0,0
Exp/Cntr=0.5,0.3

Type RM Length L Ch R = 1 ,10113   ,114.7,112.5,112.3
XS GIS Cut Line= 2
2065035.62446733331126.5409724752066033.71680792330297.231208389
#Sta/Elev= 30
       0 2455.75    23.4 2446.96    28.7 2443.56    49.1 2427.27      52 2425.65
    54.3 2424.63   100.4 2418.56   118.4 2414.56   131.2 2412.87   295.5 2411.11
   404.2 2409.06   480.3 2410.13   511.1 2411.82   524.9 2409.41   552.9 2408.35
   557.8 2408.53   566.3    2411   579.1 2412.16   608.8 2410.79     626 2408.67
   649.7 2410.45   650.7 2410.52   762.5 2411.06   869.7 2411.65   870.5 2411.67
  1002.5 2411.73  1053.8 2413.47  1101.5 2415.13  1227.5 2422.15  1297.7 2427.38
#Mann= 14 ,-1 , 0
       0      .1       0      52      .1       0   100.4     .06       0
   295.5     .06       0   480.3     .07       0   524.9    .055       0
   608.8    .045       0   649.7    .045       0   650.7     .06       0
   762.5    .055       0   869.7     .07       0   870.5    .055       0
  1053.8     .06       0  1101.5    .055       0
#XS Ineff= 2 , 0
             569    2411     688            2411
Permanent Ineff=
       F       F
Bank Sta=608.8,649.7
XS Rating Curve= 0 ,0
Exp/Cntr(USF)=0,0
Exp/Cntr=0.5,0.3

Type RM Length L Ch R = 1 ,10001   ,174.9,180.3,183.5
XS GIS Cut Line= 2
2065133.59896722331148.922649869   2066080.79671330330.201196668
#Sta/Elev= 30
       0 2435.75    12.6 2430.95      17 2428.76    26.2 2422.81    29.9  2421.2
    33.2 2420.38    47.3 2419.15    64.6 2416.06    75.1 2414.67     110 2411.65
   177.4 2410.25   459.2  2410.5   463.5  2410.3   473.5 2408.07   482.1 2408.16
   489.6 2407.64   493.8 2408.11   502.6 2410.24   523.7 2410.88   671.7  2410.5
   806.2  2411.2   858.2 2411.71   998.5 2414.58    1023 2415.49    1049 2417.03
  1100.6 2418.57  1119.5 2420.18  1157.4 2424.64  1179.1 2426.67    1252 2430.79
#Mann= 14 ,-1 , 0
       0      .1       0   85.13     .07       0  212.83    .055       0
  318.43     .07       0  396.97     .06       0  435.08     .07       0
   459.2    .045       0   502.6     .07       0   581.1     .06       0
  668.38     .07       0  765.24    .055       0  785.03     .06       0
  901.68     .07       0  980.48    .055       0
Bank Sta=459.2,502.6
XS Rating Curve= 0 ,0
Exp/Cntr(USF)=0,0
Exp/Cntr=0.5,0.3

Type RM Length L Ch R = 1 ,9820    ,476,476.9,479
XS GIS Cut Line= 2
2065133.34558145331272.2339606942066178.78989861330612.218512268
#Sta/Elev= 30
       0 2443.02     7.7 2440.48    15.4 2436.68    38.7 2427.49    52.2 2420.53
    56.9 2419.65    66.5 2419.15    78.3 2414.71    85.8 2412.61   100.8 2410.75
   267.6 2410.22   302.5 2410.87   341.3 2410.07   492.7 2410.02   504.3 2407.97
   523.7 2410.23   558.8  2410.4   585.8 2409.78     621 2410.31   661.1 2409.52
   733.2 2410.25   832.3 2410.12   977.4 2411.56  1073.6 2413.86  1097.9 2415.15
  1120.1 2415.21    1129 2414.37  1136.7 2416.28    1151  2417.7  1236.4 2423.54
#Mann= 6 ,-1 , 0
       0      .1       0  100.52    .055       0  229.97     .07       0
   492.7    .045       0   523.7     .07       0 1191.92     .05       0
Bank Sta=492.7,523.7
XS Rating Curve= 0 ,0
Exp/Cntr(USF)=0,0
Exp/Cntr=0.3,0.1

Type RM Length L Ch R = 1 ,9343    ,596.9,597.6,596.8
XS GIS Cut Line= 2
2065164.52595441331743.1686463272066569.03317321331014.905643986
#Sta/Elev= 30
       0 2482.71    64.6 2457.83   112.6 2442.11   143.5 2434.14   197.6 2423.59
     236 2421.05   255.5 2418.74   278.9 2418.03   295.8 2415.26   430.7 2408.26
     455 2409.73   645.22409.584   659.5 2408.22   670.7 2409.58   829.6 2408.88
   855.4 2409.64   878.5  2408.9  1136.5 2409.97  1277.6 2415.77    1310 2418.62
  1409.8 2422.57  1424.6 2424.49  1433.4  2427.1    1448 2432.87    1465 2441.15
    1480 2446.07  1493.2 2451.61  1513.7 2458.04  1535.4 2461.81  1582.1 2464.81
#Mann= 10 ,-1 , 0
       0    .055       0    39.8      .1       0  356.72    .055       0
   559.3     .07       0   645.2    .045       0   670.7     .07       0
 1294.48      .1       0 1295.68     .07       0 1399.04      .1       0
 1503.59    .055       0
Bank Sta=645.2,670.7
XS Rating Curve= 0 ,0
Exp/Cntr(USF)=0,0
Exp/Cntr=0.3,0.1

Type RM Length L Ch R = 1 ,8746    ,177,179.8,183.7
XS GIS Cut Line= 2
2065444.12692853332276.3612016132066705.58248615331600.116985153
#Sta/Elev= 30
       0 2513.15    41.9 2514.84    64.2 2511.56   105.2 2500.13   123.8 2493.16
   134.9 2487.27   224.3 2464.42   320.5 2439.35   339.9 2435.84   391.8 2421.59
   477.4 2411.52   514.6 2409.09   533.2 2409.57   607.7 2409.17   618.2 2407.41
   628.3 2409.34   667.3 2410.94   682.1 2408.91   909.8 2408.57  1037.9 2409.28
  1065.6 2410.63  1115.4 2418.71  1166.3 2438.21  1234.2 2455.65  1259.1 2465.85
  1277.6 2473.15  1288.9  2474.1  1307.5 2479.14  1368.1 2487.38  1431.3 2493.36
#Mann= 6 ,-1 , 0
       0      .1       0   224.3    .055       0   533.2    .055       0
   607.7    .045       0   628.3    .055       0  1259.1    .055       0
Bank Sta=607.7,628.3
XS Rating Curve= 0 ,0
Exp/Cntr(USF)=0,0
Exp/Cntr=0.5,0.3

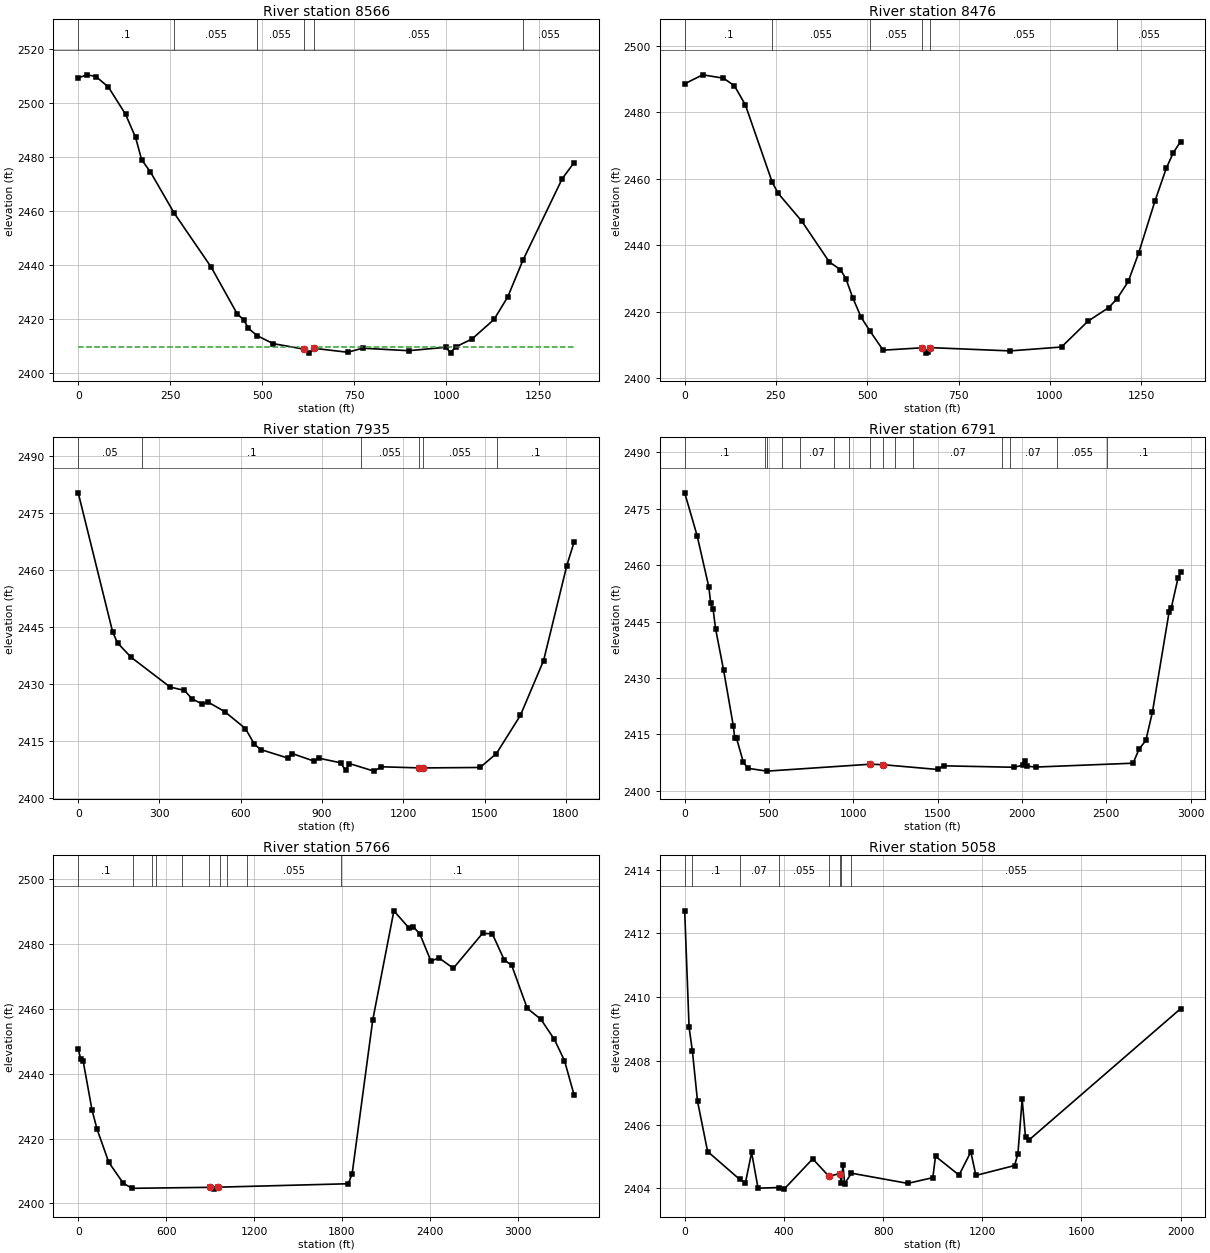
Type RM Length L Ch R = 1 ,8566    ,90,90.6,90
XS GIS Cut Line= 2
2065447.23861505332291.6497523492066759.36234098331987.917408384
#Sta/Elev= 30
       0 2509.28    24.6 2510.38    48.2 2509.74      82 2505.85   128.5 2495.81
   155.8 2487.22   172.2 2478.99   196.3 2474.41   260.3  2459.3   361.3 2439.21
   432.1 2421.89   448.9 2419.85   462.4  2416.6   485.9 2413.91   529.7 2410.95
   612.32408.959   627.4 2407.45   640.9 2409.22   731.8 2407.77   772.2 2409.28
   897.4 2408.35   997.8 2409.61  1011.3  2407.6  1024.8 2409.75  1069.2 2412.65
  1129.2  2419.9  1166.2 2428.18  1207.7 2441.81  1314.4 2471.97  1346.8 2477.95
#Mann= 6 ,-1 , 0
       0      .1       0   260.3    .055       0   485.9    .055       0
   612.3    .045       0   640.9    .055       0  1207.7    .055       0
#XS Ineff= 2 , 0
          599.04  2409.8  652.59          2409.8
Permanent Ineff=
       F       F
Bank Sta=612.3,640.9
XS Rating Curve= 0 ,0
Exp/Cntr(USF)=0,0
Exp/Cntr=0.5,0.3

Type RM Length L Ch R = 1 ,8476    ,540.2,540.8,526.3
XS GIS Cut Line= 2
2065439.13908587332356.4459857292066773.53651703332105.360581384
#Sta/Elev= 30
       0  2488.5    49.3 2491.19   106.1 2490.18   136.1 2487.91   166.1 2482.17
   239.6 2458.91   256.3  2455.5   320.9 2447.13   396.1 2434.89   426.5 2432.61
   441.4 2429.89   459.9  2424.2   483.3 2418.22   506.3 2414.29   543.4 2408.38
   651.1  2409.1   660.2 2407.49   666.9 2407.79   672.92409.145   890.6 2408.16
  1031.7 2409.33  1104.2  2417.1    1161 2421.19  1183.5 2423.81  1214.5 2429.05
  1242.5 2437.46  1287.4 2453.17  1318.3 2463.03  1337.8 2467.78  1357.8 2471.12
#Mann= 6 ,-1 , 0
       0      .1       0   239.6    .055       0   506.3    .055       0
   651.1    .045       0   672.9    .055       0  1183.5    .055       0
Bank Sta=651.1,672.9
XS Rating Curve= 0 ,0
Exp/Cntr(USF)=0,0
Exp/Cntr=0.5,0.3

Type RM Length L Ch R = 1 ,7935    ,1123.1,1143.3,1098.8
XS GIS Cut Line= 2
2065450.62927676 333375.258053362066783.61066498332120.304843968
#Sta/Elev= 30
       0 2480.22   127.4  2443.6   145.4 2440.78     195 2437.05   339.2 2429.21
   392.3 2428.33   420.6 2426.07   457.8 2424.78   478.5 2425.29   540.7 2422.76
   617.3 2418.31   650.4 2414.19   673.6  2412.8   776.2 2410.51   789.8 2411.75
   868.6  2409.8   889.5 2410.51   968.4 2409.32   986.9 2407.32  1000.9 2409.12
  1091.7 2407.13  1119.2 2408.27  1258.6 2407.98  1271.9 2407.97  1483.6 2408.09
    1544 2411.75  1632.4 2421.78    1718 2436.18  1803.6 2461.09  1830.8 2467.35
#Mann= 6 ,-1 , 0
       0     .05       0  236.66      .1       0  1042.5    .055       0
  1258.6    .045       0  1271.9    .055       0 1545.74      .1       0
Bank Sta=1258.6,1271.9
XS Rating Curve= 0 ,0
Exp/Cntr(USF)=0,0
Exp/Cntr=0.3,0.1

Type RM Length L Ch R = 1 ,6791    ,972.7,1025.1,1029.7
XS GIS Cut Line= 4
 2065706.9128301333606.2799838082066062.42871986333781.667822756
2066989.06806479333311.2650906282067058.85082007331807.585804775
#Sta/Elev= 30
       0 2479.24    73.7 2467.85   143.2  2454.2   154.2 2449.91   168.5 2448.29
   183.5 2443.01     231 2432.04   288.5 2417.22   296.9 2413.95   307.9  2413.9
   348.1 2407.55   375.4 2405.97   487.6 2405.22  1100.8 2407.06  1176.5 2406.93
  1499.5 2405.66  1535.9 2406.63  1952.6 2406.25  2008.6 2406.83  2018.5 2408.01
  2031.6 2406.53  2080.9  2406.3  2658.9 2407.33  2695.1 2411.12  2734.5 2413.37
  2773.9 2420.96  2872.4  2447.5  2885.5 2448.62    2925 2456.49  2940.9 2458.08
#Mann= 15 ,-1 , 0
       0      .1       0  474.11     .07       0  490.79      .1       0
  578.38    .055       0  682.64     .07       0   885.8    .055       0
  977.34     .07       0  1100.8    .045       0  1176.5     .07       0
 1247.84    .055       0 1354.39     .07       0 1881.46    .055       0
 1926.33     .07       0 2208.07    .055       0 2505.23      .1       0
Bank Sta=1100.8,1176.5
XS Rating Curve= 0 ,0
Exp/Cntr(USF)=0,0
Exp/Cntr=0.3,0.1

Type RM Length L Ch R = 1 ,5766    ,700.7,708.8,699.8
XS GIS Cut Line= 3
2065675.81663902333940.9472396562067664.62909673 334771.23544662
2068775.52819979334241.856270627
#Sta/Elev= 30
       0  2447.8    16.5 2444.61    33.2 2444.07    94.7 2428.73   128.5 2422.95
   208.4 2412.73     308 2406.21   368.4 2404.68   901.82404.985   930.2 2404.43
     955 2405.03  1843.9 2406.09  1870.2 2409.21    2011 2456.66  2155.2 2490.28
  2258.5 2484.96  2287.8 2485.34  2332.1 2483.16  2408.4 2474.74    2462 2475.78
  2561.1 2472.56  2760.1 2483.32  2826.9  2483.2  2908.1 2475.19  2959.8 2473.42
  3065.3 2460.22  3159.2  2456.8  3250.7 2450.61  3319.7 2444.08  3385.8 2433.42
#Mann= 10 ,-1 , 0
       0      .1       0   372.9    .055       0  504.14     .07       0
  529.46    .055       0  711.39     .07       0   895.5    .045       0
   968.6    .055       0 1018.43     .07       0 1153.03    .055       0
 1791.01      .1       0
Bank Sta=901.8,955
XS Rating Curve= 0 ,0
Exp/Cntr(USF)=0,0
Exp/Cntr=0.3,0.1

Type RM Length L Ch R = 1 ,5058    ,713.9,725,700
XS GIS Cut Line= 2
2065608.22015488334726.4560663662067542.84877737335232.626957964
#Sta/Elev= 30
       0 2412.71    17.7 2409.06    31.3  2408.3    51.7 2406.74    92.5 2405.16
   221.2 2404.29     245 2404.18   269.9 2405.13   295.8 2404.01   380.6 2404.03
     401 2403.98   516.3 2404.93   581.7 2404.38   624.8 2404.47   631.6 2404.18
   638.2 2404.73   645.1 2404.15   672.3 2404.48   899.5 2404.16  1000.5 2404.34
  1011.4 2405.01  1106.3 2404.42  1153.8 2405.15  1174.2 2404.41  1330.2 2404.72
  1343.7 2405.09  1360.7  2406.8  1374.3 2405.61  1388.1 2405.52  1999.7 2409.64
#Mann= 8 ,-1 , 0
       0      .1       0    31.3      .1       0   221.2     .07       0
   380.6    .055       0   581.7    .045       0   624.8    .055       0
   631.6     .07       0   672.3    .055       0
Bank Sta=581.7,624.8
XS Rating Curve= 0 ,0
Exp/Cntr(USF)=0,0
Exp/Cntr=0.3,0.1