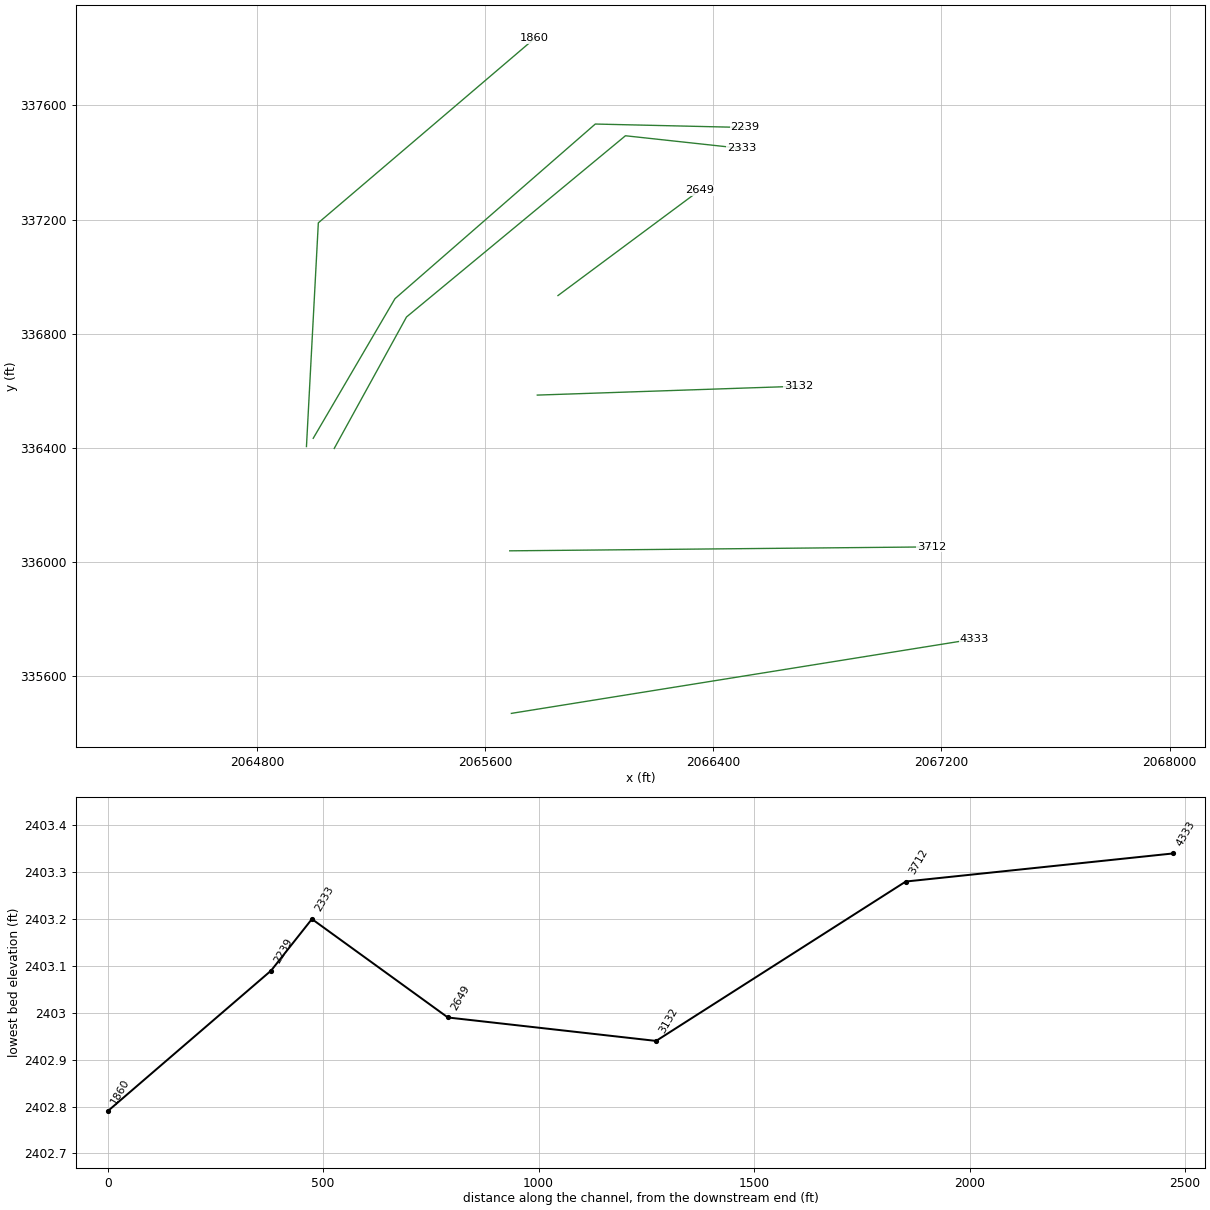
HEC-RAS study MTHODSTBR.prj: MTHODSTBR

--- MTHODSTBR.g01 (geometry) --- (continued)

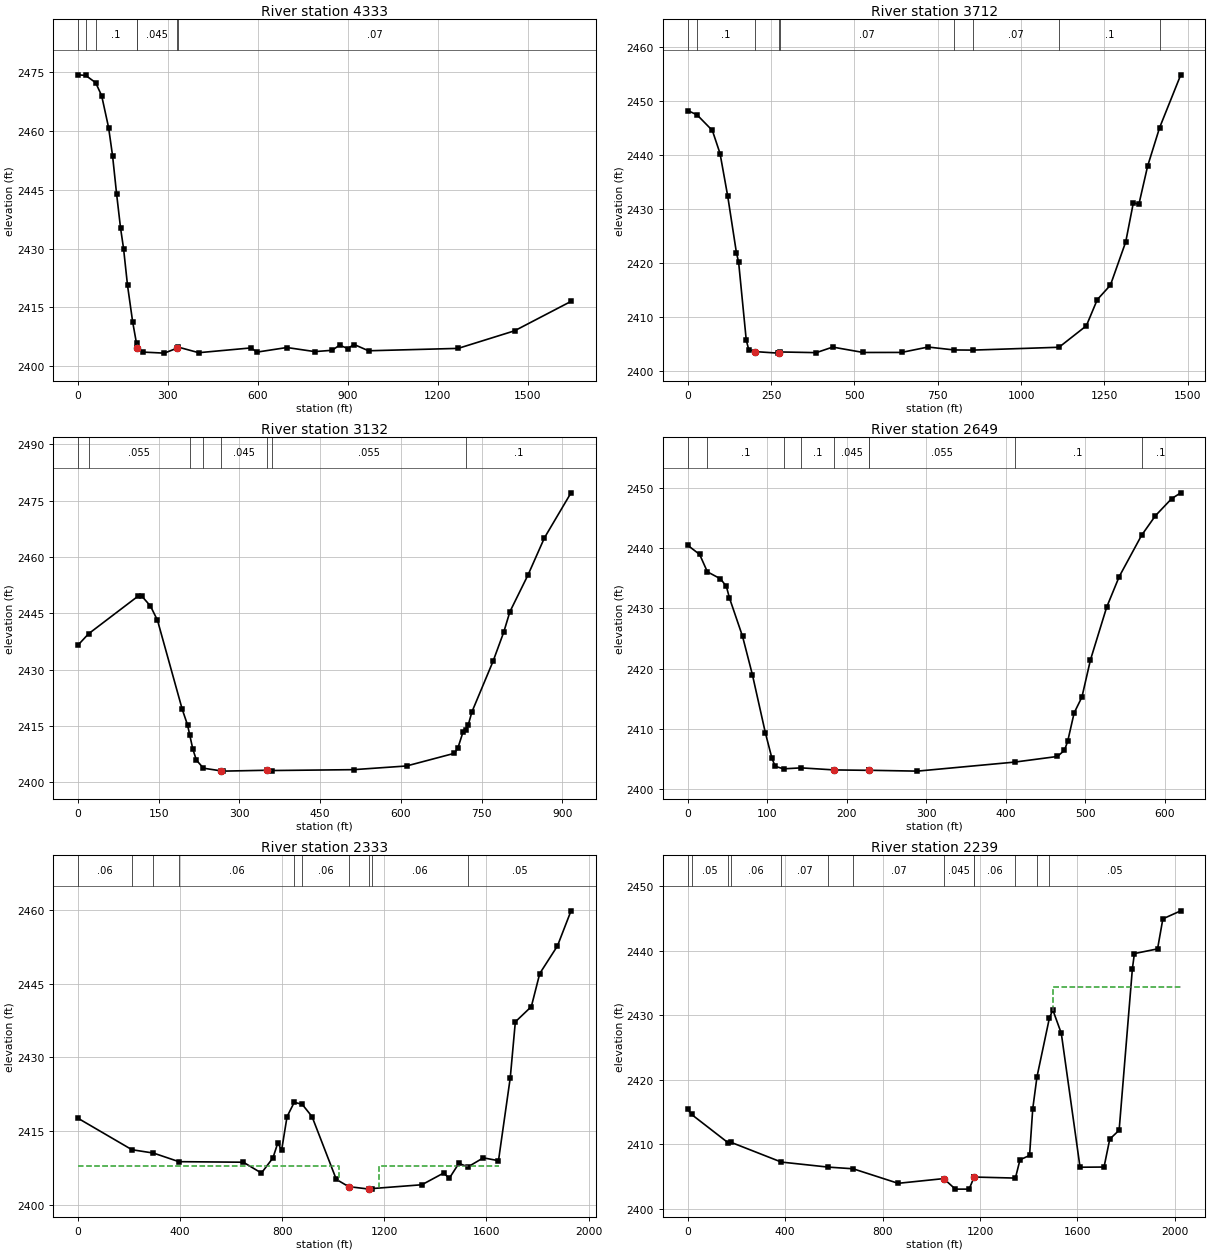
Type RM Length L Ch R = 1 ,4333    ,563.7,621.1,570.6
XS GIS Cut Line= 2
  2065692.064413 335468.633017852067316.15874616335729.481820881
#Sta/Elev= 30
       0 2474.35    25.5 2474.19    58.7 2472.35    78.7 2469.03   101.9 2460.88
   115.2 2453.65   128.5 2444.01   141.8 2435.24   151.8 2430.03     165 2420.64
   182.2 2411.29     195 2405.82   198.3 2404.71   218.2  2403.6   287.8 2403.34
   331.2 2404.64   334.5 2404.87   402.6 2403.45   577.1 2404.67     597  2403.6
   696.7 2404.77   789.8 2403.73   847.6 2404.06   872.8 2405.38   899.4 2404.52
   921.2 2405.54   969.2 2403.94  1268.3 2404.55  1456.3 2409.03  1644.9 2416.54
#Mann= 7 ,-1 , 0
       0     .05       0    25.5      .1       0    58.7      .1       0
     195     .07       0   198.3    .045       0   331.2    .045       0
   334.5     .07       0
Bank Sta=198.3,331.2
XS Rating Curve= 0 ,0
Exp/Cntr(USF)=0,0
Exp/Cntr=0.3,0.1

Type RM Length L Ch R = 1 ,3712    ,579.5,579.4,585.9
XS GIS Cut Line= 2
2065686.18348236336038.505209869 2067165.1864663336052.327667663
#Sta/Elev= 30
       0 2448.29    27.8 2447.49    73.7 2444.59    96.7 2440.32   119.7 2432.42
   145.9  2421.9   152.5 2420.14   175.4 2405.67   182.8 2403.94   202.7 2403.56
   270.6 2403.28   273.9 2403.39   275.5  2403.5   385.4 2403.37   434.7  2404.4
   526.5  2403.4   641.3 2403.41   720.8 2404.41   798.8 2403.87   855.1 2403.84
  1113.8 2404.37  1195.8 2408.35  1228.6 2413.21    1268 2415.89  1313.9 2423.91
  1336.9 2431.21  1353.3 2430.86  1379.6 2437.97  1415.6 2445.12  1479.1 2454.92
#Mann= 9 ,-1 , 0
       0     .05       0    27.8      .1       0   202.7    .045       0
   273.9    .045       0   275.5     .07       0   798.8    .055       0
   855.1     .07       0  1113.8      .1       0  1415.6     .05       0
Bank Sta=202.7,273.9
XS Rating Curve= 0 ,0
Exp/Cntr(USF)=0,0
Exp/Cntr=0.3,0.1

Type RM Length L Ch R = 1 ,3132    ,470,483.1,499.2
XS GIS Cut Line= 2
2065782.94068692336584.4922927262066698.67851576336615.592822762
#Sta/Elev= 30
       0 2436.52    19.6 2439.53   111.5 2449.54   118.1 2449.61   134.5 2446.92
   147.6 2443.13   193.6 2419.42   203.5 2415.23   207.7 2412.48   213.3 2408.82
   219.9 2405.89     233 2403.72   266.2    2403   269.1 2402.94   350.4 2403.17
     361  2403.1     512 2403.33   610.5 2404.31   699.1 2407.67   705.7 2408.97
   715.6 2413.38   720.2 2413.89   725.4  2415.3     732 2418.69   771.4  2432.2
   791.1  2439.9   802.7  2445.4   836.4  2455.2   866.9 2465.08   916.3 2477.06
#Mann= 8 ,-1 , 0
       0      .1       0    19.6    .055       0   207.7    .025       0
     233    .045       0   266.2    .045       0   350.4    .045       0
     361    .055       0   720.2      .1       0
Bank Sta=266.2,350.4
XS Rating Curve= 0 ,0
Exp/Cntr(USF)=0,0
Exp/Cntr=0.3,0.1

Type RM Length L Ch R = 1 ,2649    ,318.5,315.5,309
XS GIS Cut Line= 2
2065855.50859034 336933.509352022066353.11707092337303.260098005
#Sta/Elev= 30
       0 2440.43    14.9 2438.92    24.6 2436.04    41.1 2434.88    48.5 2433.62
    52.4 2431.69    68.8 2425.35    81.2 2418.99    97.5 2409.36   105.7 2405.16
   109.8 2403.79   120.4 2403.37   142.5 2403.53   184.1 2403.19   228.1 2403.12
   228.2 2403.13   288.7 2402.99   411.2 2404.49   464.7 2405.42   473.6 2406.43
   477.7 2407.94   485.8 2412.64   495.6 2415.27   506.3 2421.42   526.7 2430.17
   542.5 2435.25   570.6 2442.09     588 2445.34   608.4 2448.17   619.9 2449.14
#Mann= 9 ,-1 , 0
       0     .05       0    24.6      .1       0   120.4    .045       0
   142.5      .1       0   184.1    .045       0   228.1    .045       0
   228.2    .055       0   411.2      .1       0   570.6      .1       0
Bank Sta=184.1,228.1
XS Rating Curve= 0 ,0
Exp/Cntr(USF)=0,0
Exp/Cntr=0.5,0.3

Type RM Length L Ch R = 1 ,2333    ,96.7,94.7,91.2
XS GIS Cut Line= 4
2065070.93396879336397.3633361622065324.36478613336858.313590885
2066092.00305893337493.7270894292066498.51171084337449.551791614
#Sta/Elev= 30
       0 2417.62   211.1 2411.22   295.4 2410.54     395 2408.79   647.5 2408.68
   718.4 2406.47   763.5 2409.55   782.7 2412.62   797.5 2411.11   818.8 2417.95
   847.1 2420.88   878.2 2420.46   916.8 2417.95  1011.7 2405.19    1060 2403.71
  1141.5  2403.2  1150.9 2403.31    1347 2404.09  1432.8 2406.49  1454.2 2405.38
  1491.8 2408.43  1528.1 2407.74  1587.8 2409.57  1647.2 2408.99  1693.4  2425.9
  1713.2 2437.25  1775.9 2440.35  1808.9 2447.09  1878.2  2452.7  1931.4 2459.85
#Mann= 10 ,-1 , 0
       0     .06       0   211.1     .05       0   295.4    .055       0
     395     .06       0   847.1    .055       0   878.2     .06       0
    1060    .045       0  1141.5    .045       0  1150.9     .06       0
  1528.1     .05       0
#XS Ineff= 2 ,-1
       0 1022.75    2408 1177.59  1649.7    2408
Permanent Ineff=
       F       F
Bank Sta=1060,1141.5
XS Rating Curve= 0 ,0
Exp/Cntr(USF)=0,0
Exp/Cntr=0.5,0.3

Type RM Length L Ch R = 1 ,2239    ,375.2,379.3,396.6
XS GIS Cut Line= 4
2064997.35749315336433.0833079922065283.96277177336922.589522819
2065986.23664565 337534.801246392066511.34667834337522.711033233
#Sta/Elev= 30
       0 2415.44    15.2 2414.66   166.5 2410.24   178.5 2410.32     384 2407.28
   576.2  2406.5   678.6 2406.24   863.5 2403.99  1050.7 2404.72  1098.5 2403.09
  1155.1 2403.09  1175.4 2404.94  1176.9 2404.96  1345.1  2404.8    1364 2407.64
  1403.2  2408.3  1416.3 2415.53  1433.7 2420.48  1484.9 2429.62  1498.9 2430.82
  1533.6 2427.21  1610.5 2406.48    1709 2406.51  1732.5 2410.83    1771 2412.21
  1825.4  2437.2  1833.7 2439.56  1928.8 2440.29  1950.6 2444.94  2024.1 2446.18
#Mann= 13 ,-1 , 0
       0     .06       0    15.2     .05       0   166.5     .07       0
   178.5     .06       0     384     .07       0   576.2     .06       0
   678.6     .07       0  1050.7    .045       0  1175.4    .045       0
  1176.9     .06       0  1345.1     .05       0  1433.7     .06       0
  1484.9     .05       0
#XS Ineff= 2 , 0
                         1499.63         2434.44
Permanent Ineff=
       F       F
Bank Sta=1050.7,1175.4
XS Rating Curve= 0 ,0
Exp/Cntr(USF)=0,0
Exp/Cntr=0.5,0.3

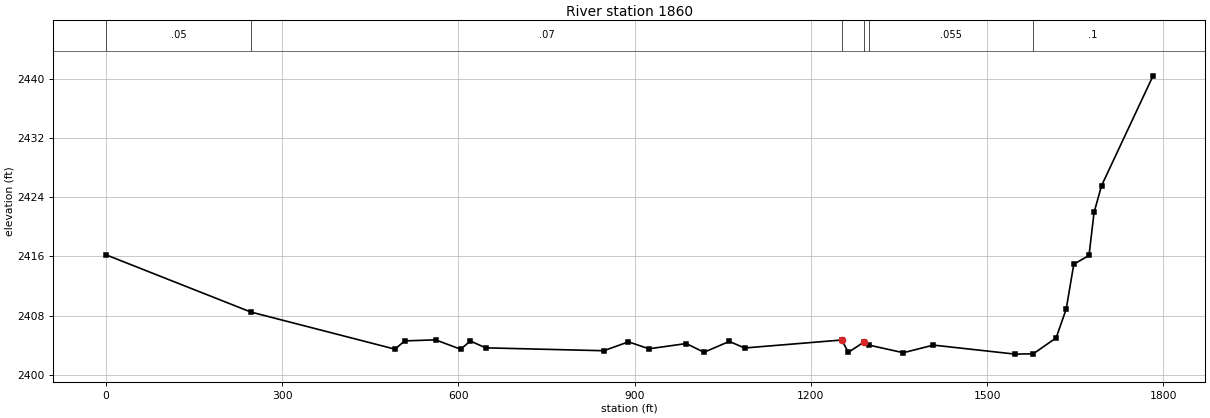
Type RM Length L Ch R = 1 ,1860    ,1842,1842,1842
XS GIS Cut Line= 3
2064973.62543319 336404.071152152065015.24740217337188.460305716
2065773.93174152337835.273854337
#Sta/Elev= 30
       0 2416.23     247 2408.48   492.3 2403.46   508.7 2404.58   561.3 2404.72
     604 2403.45   620.5 2404.56   646.7 2403.64   847.7 2403.25   889.6 2404.45
   924.5 2403.51     988 2404.22  1018.2 2403.04  1061.3 2404.51  1087.2 2403.62
  1252.7  2404.7  1263.9 2403.03    1290  2404.4  1298.4 2404.02  1357.4 2402.98
  1408.6 2404.01  1547.9 2402.79  1578.7 2402.84  1617.5 2404.98  1634.7 2408.89
  1647.6 2414.95  1673.5 2416.13  1682.1 2421.94  1694.8 2425.56  1782.5 2440.42
#Mann= 6 ,-1 , 0
       0     .05       0     247     .07       0  1252.7    .045       0
    1290    .045       0  1298.4    .055       0  1578.7      .1       0
Bank Sta=1252.7,1290
XS Rating Curve= 0 ,0
Exp/Cntr(USF)=0,0
Exp/Cntr=0.3,0.1
LCMann Table=0

Chan Stop Cuts=-1
Use User Specified Reach Order=0
Composite Channel Slope=5